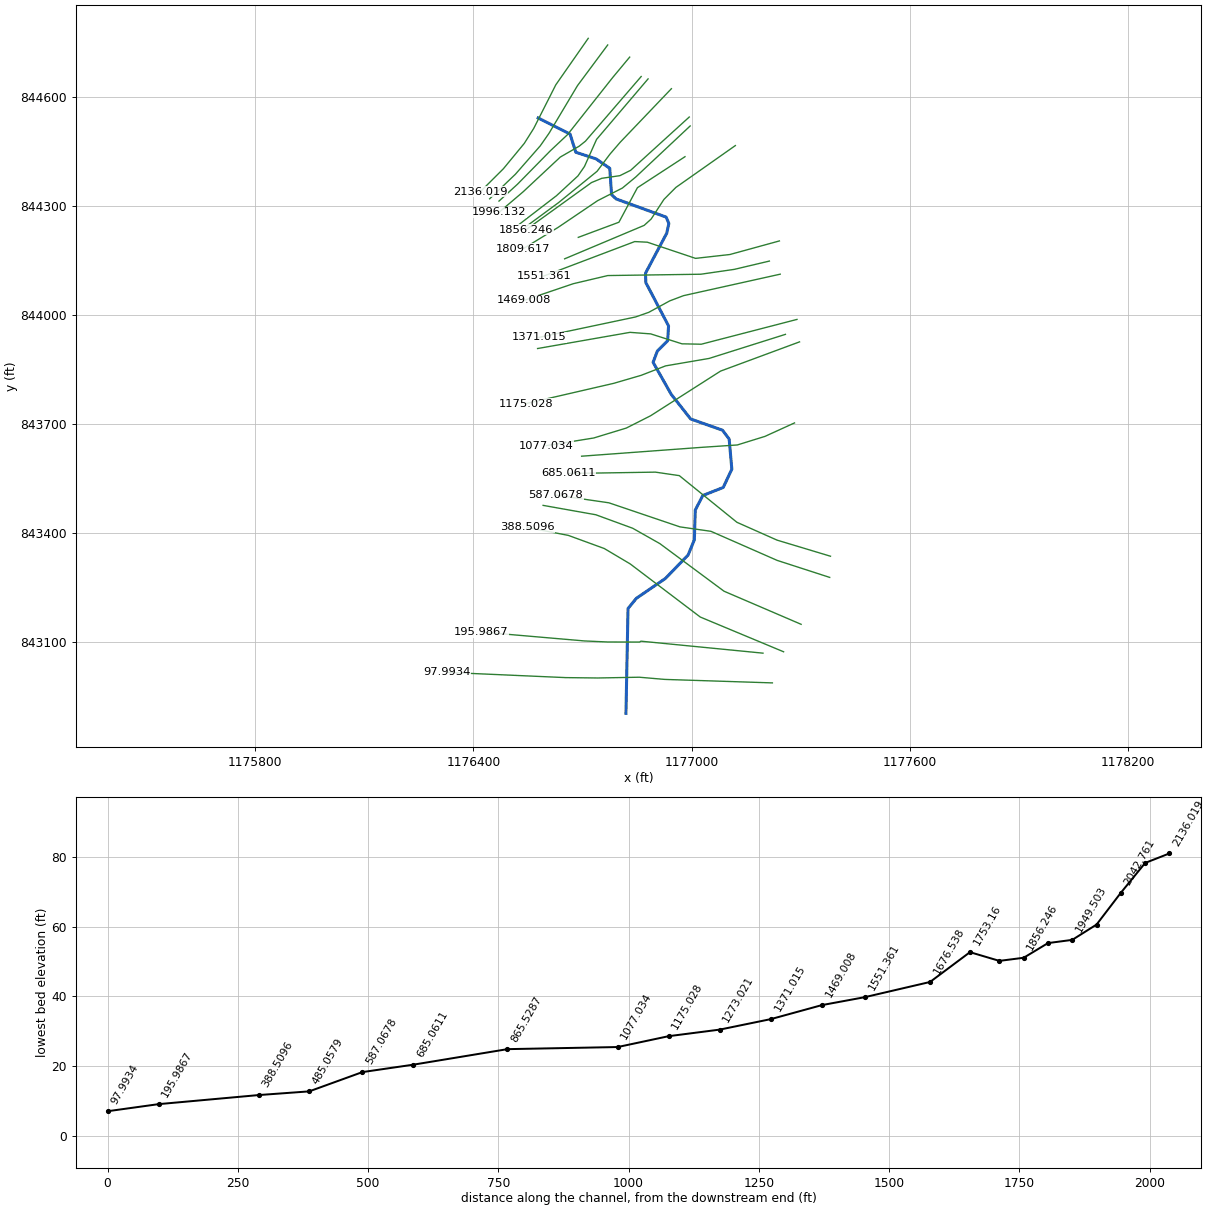
--- 140_ras.prj (project) ---

Proj Title=140
Current Plan=p01
Default Exp/Contr=0.3,0.1
English Units
Geom File=g01
Flow File=f01
Plan File=p01
Y Axis Title=Elevation
X Axis Title(PF)=Main Channel Distance
X Axis Title(XS)=Station
BEGIN DESCRIPTION:
RFD model 140 exported to HEC-RAS
END DESCRIPTION:

--- 140_ras.p01 (plan) ---

Plan Title=Plan 01
Program Version=4.10
Short Identifier=Plan 01
Geom File=g01
Flow File=f01
Subcritical Flow
Calc Critical at every XS
Secant Critical Depth

--- 140_ras.f01 (steady flow) ---

Flow Title=Flow 01
Program Version=5.01
Number of Profiles= 5
Profile Names=10yr,25yr,50yr,100yr,500yr
River Rch & RM=140,23,2136.019
   209.4  376.76  541.91  743.43 1361.15
River Rch & RM=140,23, 2089.39
  217.36   391.4  563.41  773.58 1419.56
River Rch & RM=140,23,1996.132
  221.03  398.16  573.33  787.51 1446.59
River Rch & RM=140,23,1902.874
  225.92  407.17  586.57  806.09  1482.7
River Rch & RM=140,23,1809.617
  235.09  424.05  611.41  840.97 1550.61
River Rch & RM=140,23,1551.361
   284.4  515.14  745.72 1030.16 1921.52
River Rch & RM=140,23,1469.008
  288.04  521.89  755.69 1044.22 1949.25
River Rch & RM=140,23,1273.021
  308.04  558.96  810.51 1121.68 2102.41
River Rch & RM=140,23,1175.028
  312.28  566.82  822.14 1138.13 2135.02
River Rch & RM=140,23,1077.034
  321.97  584.79  848.75 1175.77 2209.73
River Rch & RM=140,23,865.5287
   326.2  592.64  860.39 1192.25 2242.48
River Rch & RM=140,23,685.0611
  335.27  609.48  885.34  1227.6  2312.8
River Rch & RM=140,23,587.0678
  336.47  611.73  888.67 1232.31 2322.19
River Rch & RM=140,23,485.0579
  337.08  612.85  890.34 1234.67 2326.89
River Rch & RM=140,23,388.5096
  337.68  613.97     892 1237.03 2331.58
River Rch & RM=140,23,195.9867
  338.29  615.09  893.66 1239.38 2336.28
River Rch & RM=140,23, 97.9934
  433.36  792.25 1157.05 1613.69 3087.97
Boundary for River Rch & Prof#=140,23,1
Up Type= 0
Dn Type= 2
Boundary for River Rch & Prof#=140,23,2
Up Type= 0
Dn Type= 2
Boundary for River Rch & Prof#=140,23,2
Up Type= 0
Dn Type= 2
Boundary for River Rch & Prof#=140,23,2
Up Type= 0
Dn Type= 2
Boundary for River Rch & Prof#=140,23,2
Up Type= 0
Dn Type= 2

--- 140_ras.g01 (geometry) ---

Geom Title=140
Program Version=4.10

River Reach=140,23
Reach XY= 30
1176578.19284633844541.8233962061176665.69281939 844497.65674004
1176681.52614665844447.6567543451176737.35946307844429.323424816
1176774.85945129844403.4900980141176779.85944775844330.990119353
1176792.35944372844319.3234557211176929.85940188844269.323466539
1176937.35939917844251.8234715011176931.52606681844225.156812891
1176873.19274744844115.1568470451176874.02607974844089.323521271
1176936.52605799843970.1568880231176934.02605751843929.323566854
1176905.69273171843900.9902427051176894.02606755843870.156918809
1176944.02605033843781.8236101421176997.35936603843714.323628515
1177084.85933951843683.4903017731177103.09997141843659.199077293
1177110.49345341843576.3920792791177086.83431107843526.116401911
1177030.64384815843503.9359560161177009.94209868843464.011153385
1177007.48247677843382.3179049641176990.32370961843340.493410021
1176928.12317869843276.1480331721176848.06181103843221.357075319
1176825.10504952843193.4097134621176819.38883781842905.007060185

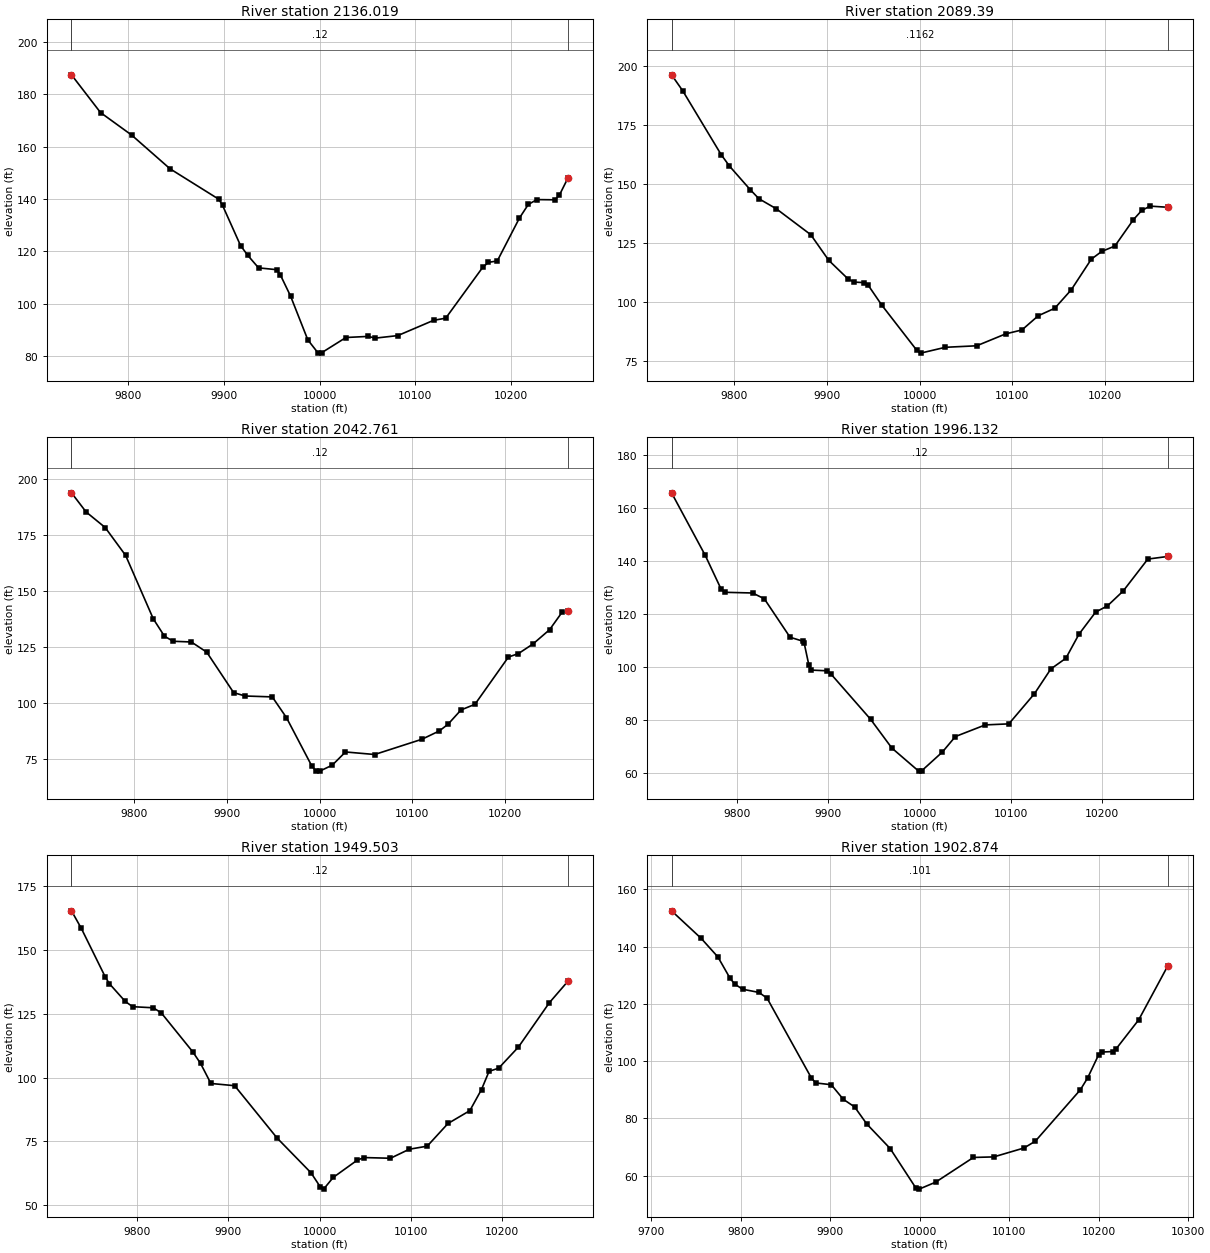
Type RM Length L Ch R = 1 ,2136.019,46.628900,46.628900,46.628900
XS GIS Cut Line= 6
1176715.68950532844760.8165462171176626.55787798844633.035330465
1176565.74528423844513.0114593621176539.87648522844471.990332556
 1176482.4914394844402.3239411331176419.52973005844339.680341927
#Sta/Elev= 30
9740.918 187.4349771.229173.01829803.817164.38469843.823151.52259894.776 139.875
9898.619137.54779917.426122.1952 9924.98118.43389936.233113.6647 9955.04112.9735
9958.789111.11939969.616102.90679987.66286.147589998.48981.0815210002.0681.22219
10027.4687.0516210050.4687.4707910058.2286.82188 10081.687.78135   1011993.62181
10131.6394.4322610170.23113.852610176.21115.765210185.47116.308710208.61132.7143
10217.86137.898510226.83139.751210245.63139.676710250.26141.423510259.04147.8655
#Mann= 3 , 0 , 0
9740.918    0.12       09740.918    0.12       010259.04    0.12       0
#XS Ineff= 2 , 0
       0                               0
Bank Sta=9740.918,10259.04
Exp/Cntr=0.3,0.1

Type RM Length L Ch R = 1 , 2089.39,46.628800,46.628800,46.628800
XS GIS Cut Line= 6
1176769.25685722844742.6186141831176686.15270377844630.779765035
 1176608.0455279844500.0105647731176583.82027883844465.248097878
1176515.31197325844387.0337492021176444.73093588844319.651483576
#Sta/Elev= 30
9732.134 196.1319744.149189.39379785.708162.33249794.666157.49439816.954147.5622
9826.433143.68699845.273139.41989882.398128.46199901.839117.60469922.666109.7308
9929.056108.41389940.383108.1691 9944.14107.2219 9959.1798.596719996.74479.58317
   1000178.3378310027.6580.8043710061.5381.4469910092.8486.4916610110.3888.15161
10127.9394.1481110145.7797.3301310163.61105.148310185.21118.104610196.43121.3703
10210.68123.664810230.57134.778210239.64138.727310248.69140.560610267.84140.0716
#Mann= 3 , 0 , 0
9732.134  0.1162       09732.134  0.1162       010267.84  0.1162       0
#XS Ineff= 2 , 0
       0                               0
Bank Sta=9732.134,10267.84
Exp/Cntr=0.3,0.1

Type RM Length L Ch R = 1 ,2042.761,46.628800,46.628800,46.628800
XS GIS Cut Line= 6
  1176829.592078844709.1866926241176782.37237045844652.397154263
1176658.62964725  844495.89230351176611.89614538844452.068845395
1176521.20983431844359.7705651111176470.31054861844313.364951211
#Sta/Elev= 30
9732.124193.75989747.915 185.2399768.504178.29929790.583165.87189820.437137.6182
9832.497 129.8849841.878127.62969861.537127.31259878.132122.77769907.173104.7454
9919.619103.24789948.883102.84759964.11393.665929991.57972.044089995.848 69.9729
10000.1169.7778610013.6272.4259210027.9278.3169610059.4177.1841210110.4883.98002
10129.2187.6823910138.5790.6484110152.6197.02737 10167.799.5592610203.84 120.614
10214.56122.123610230.48126.477110248.24 132.78210261.56140.465310267.86141.2735
#Mann= 3 , 0 , 0
9732.124    0.12       09732.124    0.12       010267.86    0.12       0
#XS Ineff= 2 , 0
       0                               0
Bank Sta=9732.124,10267.86
Exp/Cntr=0.3,0.1

Type RM Length L Ch R = 1 ,1996.132,46.628900,46.628900,46.628900
XS GIS Cut Line= 6
1176861.26312723844655.8587318631176708.02613686844478.070317492
1176690.93047135844464.3629230071176638.91650058  844434.4321691
1176536.64875385844338.8343922781176470.50193625844282.577218552
#Sta/Elev= 30
9728.144165.76129764.928142.21179782.347129.44799786.733128.18869816.932 127.927
 9829.75125.73599857.979111.2108 9872.48109.66939873.341109.13849878.462100.8819
9881.02698.809169898.11898.53919 9902.3997.47243 9946.1180.259359969.49469.35514
9998.87660.6422310002.4760.8562810024.8167.83916 10039.173.7033210071.8478.10354
10097.6678.4895310125.74 89.8929 10143.799.2453510160.12103.264410174.53112.3822
10192.77120.717110205.69123.061910222.92128.668910249.93140.737710271.85141.7297
#Mann= 3 , 0 , 0
9728.144    0.12       09728.144    0.12       010271.85    0.12       0
#XS Ineff= 2 , 0
       0                               0
Bank Sta=9728.144,10271.85
Exp/Cntr=0.3,0.1

Type RM Length L Ch R = 1 ,1949.503,46.628800,46.628800,46.628800
XS GIS Cut Line= 6
1176880.20685659844649.3429314691176738.62095826844482.993684606
1176705.36809194844408.5342647481176687.39985548844382.569276571
1176628.33861422844328.1141960071176524.34647368844248.197208506
#Sta/Elev= 30
9728.177 165.3459738.951158.46339765.223139.39729769.602136.81829787.116129.8078
9795.142127.76429817.766127.33259826.524125.34139861.133110.01689869.584105.4983
9880.87797.665089906.90696.785579953.41376.260599990.49762.6609810000.8857.02234
10004.3756.2382410014.8660.8195610041.4667.6639110048.8268.6150310077.6168.33963
10098.1271.8709110117.8473.0851910140.59 81.969610164.5387.00991 10177.395.29587
10185.57102.415510196.09103.659110217.71111.927410251.56129.293810271.77137.6565
#Mann= 3 , 0 , 0
9728.177    0.12       09728.177    0.12       010271.77    0.12       0
#XS Ineff= 2 , 0
       0                               0
Bank Sta=9728.177,10271.77
Exp/Cntr=0.3,0.1

Type RM Length L Ch R = 1 ,1902.874,46.628800,46.628800,46.628800
XS GIS Cut Line= 6
1176944.31212614844622.3547178441176803.56589257844475.128865881
1176775.29885511 844442.300946711176740.01793774844395.293862538
1176634.01437558844309.0990733391176543.86992305 844242.72748837
#Sta/Elev= 30
9722.749152.45179755.781142.85229774.506136.36089788.221128.84299793.231126.9236
9802.019125.09389820.417123.96589829.456121.96769879.046 94.07179883.86292.37917
9901.16891.757979914.61486.671219927.23584.015159940.99478.002619966.97169.49092
 9995.3455.875649999.34355.3153110017.7957.7436910059.9966.3726810082.7366.56215
10116.5569.6755210129.2472.0718610179.45 89.975310187.5994.1037510199.82102.1525
10203.89103.163810216.11103.342810219.25104.198410244.63114.386610277.22133.2681
#Mann= 3 , 0 , 0
9722.749   0.101       09722.749   0.101       010277.22   0.101       0
#XS Ineff= 2 , 0
       0                               0
Bank Sta=9722.749,10277.22
Exp/Cntr=0.3,0.1

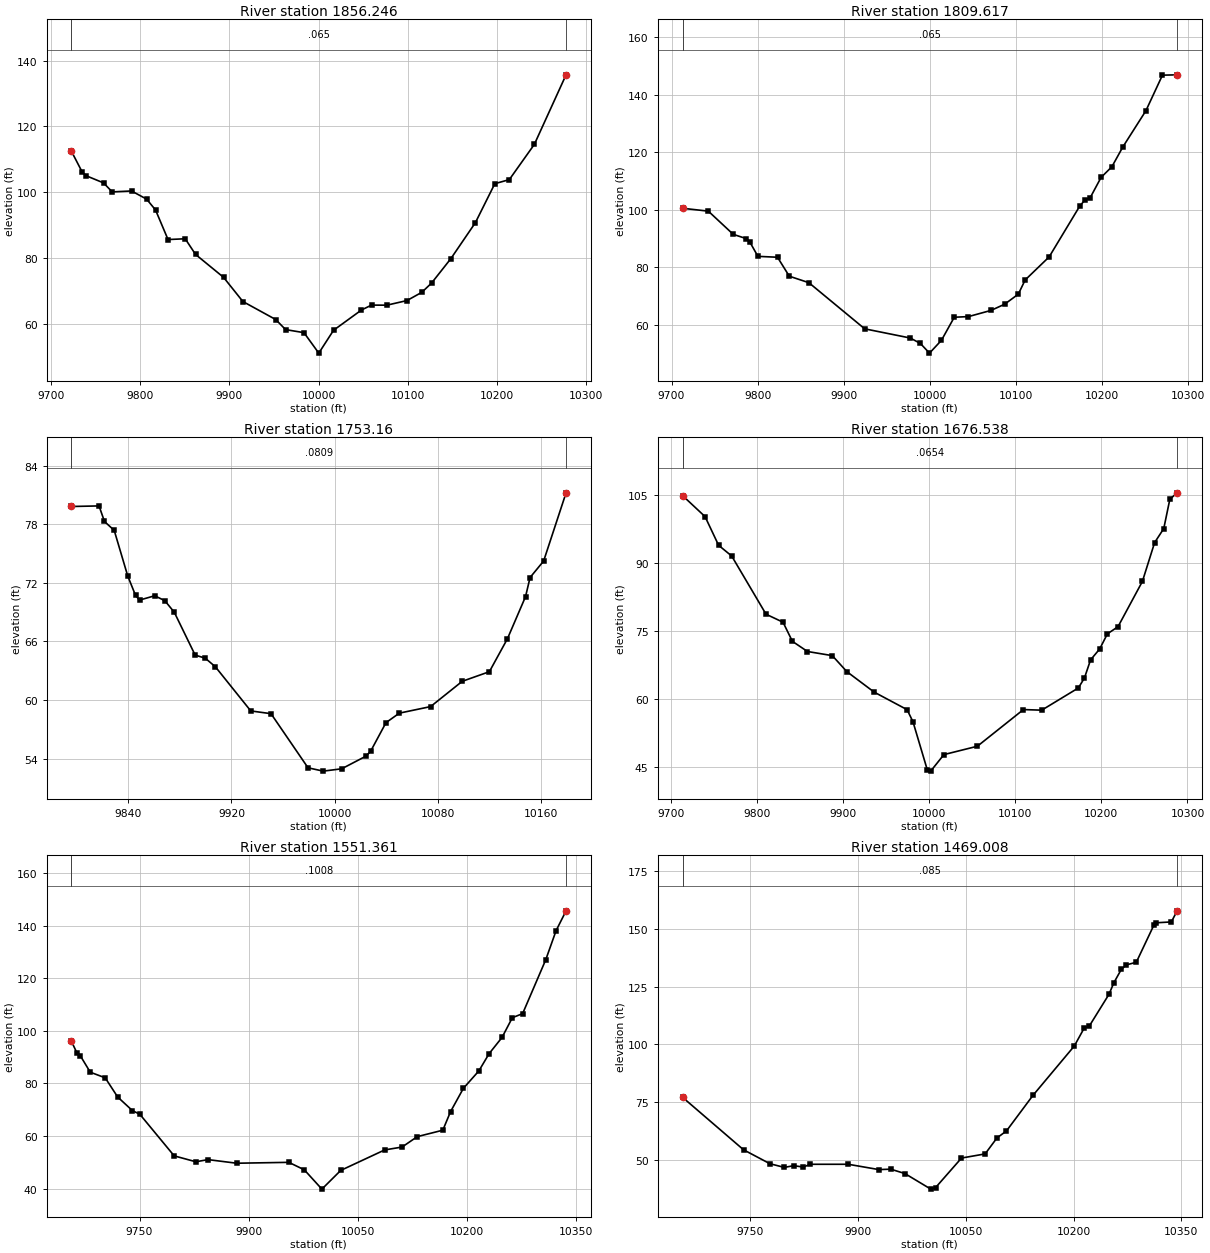
Type RM Length L Ch R = 1 ,1856.246,46.628800,46.628800,46.628800
XS GIS Cut Line= 6
1176993.42058582844544.5025564641176832.20064562844397.926228006
1176802.67052495844383.2415394171176753.23416788844376.096634997
1176724.61990139844364.2665419051176544.30726279844234.314021584
#Sta/Elev= 30
9722.837112.48089734.892 106.1589739.704104.98029758.826102.84699768.577100.1062
 9790.22100.38979807.07397.920089817.128 94.61789831.13385.622659850.38185.85934
9861.97781.10087 9893.3774.133499915.00466.788019951.80161.310249962.89258.24864
9983.47557.3206810000.0951.0979110016.6258.0414610047.9264.2058310059.1765.69606
10076.3765.67435 10098.967.07519 10115.569.5757310126.4372.3731510148.1479.83432
 10175.690.7601110197.37102.605810213.61103.837610241.67114.550110277.21135.6927
#Mann= 3 , 0 , 0
9722.837   0.065       09722.837   0.065       010277.21   0.065       0
#XS Ineff= 2 , 0
       0                               0
Bank Sta=9722.837,10277.21
Exp/Cntr=0.3,0.1

Type RM Length L Ch R = 1 ,1809.617,56.457200,56.457200,56.457200
XS GIS Cut Line= 6
1176995.92729278844519.9342024481176846.07797955  844379.4110568
1176809.59232702844349.2215454961176741.40877379844314.489317672
1176632.07793254844240.5638586371176535.81998726844181.852172194
#Sta/Elev= 30
9712.786100.54789742.76799.546959771.68191.48503 9786.9389.989289791.28588.65091
9800.332 83.83419823.10783.526289836.77376.941339859.54874.678749924.343 58.6492
9977.25855.454719988.94153.583959999.59250.2029410013.4854.6569210028.3662.67583
10044.8262.8984610071.0665.05306 10086.9 67.207910102.7470.6984910110.6675.61781
10138.5483.6474310174.03101.276510179.92103.370410186.22104.217310198.82111.2599
10211.42114.987310224.02121.8091 10250.9134.448210270.11146.806710287.22146.9236
#Mann= 3 , 0 , 0
9712.786   0.065       09712.786   0.065       010287.22   0.065       0
#XS Ineff= 2 , 0
       0                               0
Bank Sta=9712.786,10287.22
Exp/Cntr=0.3,0.1

Type RM Length L Ch R = 1 , 1753.16,76.622100,76.622100,76.622100
XS GIS Cut Line= 4
1176981.74432603844435.4372393491176850.90364918844350.143823564
 1176800.0552457844255.2617509961176688.35162479844213.661781833
#Sta/Elev= 30
9796.03279.843719817.43879.902859821.63878.306279829.18877.393149839.66172.71456
9845.66970.736969848.76970.244559860.51970.688579868.35170.187059875.70868.99638
 9891.8564.606499899.68264.288739907.51563.40598 9934.9358.879229950.59558.59732
 9979.2653.048329991.01452.7058110005.3252.9441110023.9354.2283210027.6554.72213
10039.6357.6771610049.9858.6519810074.1859.3235810098.6861.9170110119.6962.90211
10133.6966.28622 10147.770.60277 10151.272.56107 10161.774.2506410179.0781.24542
#Mann= 3 , 0 , 0
9796.032  0.0809       09796.032  0.0809       010179.07  0.0809       0
#XS Ineff= 2 , 0
       0                               0
Bank Sta=9796.032,10179.07
Exp/Cntr=0.3,0.1

Type RM Length L Ch R = 1 ,1676.538,125.176800,125.176800,125.176800
XS GIS Cut Line= 6
1177120.17929287844466.0519624791176956.67905225844350.999365975
1176923.83680551844318.0309981471176888.68788074844264.053125317
1176869.42333309844246.5881966941176650.82566884844154.664880076
#Sta/Elev= 30
9713.631104.89259739.823100.24699755.55193.926199770.731 91.56619810.60278.73518
9830.35476.970799841.21972.75467 9858.7670.513469887.56369.602619904.49666.07214
9936.13461.565519974.42257.691819981.286 55.00739998.00644.3423310001.8444.14193
10017.1547.7829810056.0349.6284510109.5257.7127510130.7857.5796110173.2962.47551
10180.3764.6750610187.4668.6610110198.0871.07808   1020774.4016410219.3475.98212
10247.6885.9705410261.8594.5226410272.4797.6122710279.56104.096310288.05105.4941
#Mann= 3 , 0 , 0
9713.631  0.0654       09713.631  0.0654       010288.05  0.0654       0
#XS Ineff= 2 , 0
       0                               0
Bank Sta=9713.631,10288.05
Exp/Cntr=0.3,0.1

Type RM Length L Ch R = 1 ,1551.361,82.352800,82.352800,82.352800
XS GIS Cut Line= 6
1177241.24916386844203.8441719821177105.25795669844166.530335543
1177010.76777544844155.9052425191176878.12308127844200.362570159
1176843.52291668844202.085781943 1176593.4946866844107.349517497
#Sta/Elev= 30
9656.21496.07176 9663.7691.676039668.43790.58334 9682.1684.302929702.74482.15642
9719.89774.853799740.22469.66354 9750.3668.287929797.65952.438949827.554 50.1919
9844.16251.01326 9883.6749.638929955.41549.978039976.68747.1343110000.9139.77796
10026.8346.9005710087.3254.7055110111.2655.8007910132.1559.7635610167.3262.21542
10177.9469.2716310195.6678.1727310216.91 84.787110231.0891.39052 10248.897.52952
10262.97105.046510277.14106.599310309.02127.154910323.19138.201310336.91145.7419
#Mann= 3 , 0 , 0
9656.214  0.1008       09656.214  0.1008       010336.91  0.1008       0
#XS Ineff= 2 , 0
       0                               0
Bank Sta=9656.214,10336.91
Exp/Cntr=0.3,0.1

Type RM Length L Ch R = 1 ,1469.008,97.993400,97.993400,97.993400
XS GIS Cut Line= 6
1177213.75670208 844148.491057071177117.30541294844125.673468166
1177025.08537286844112.2960757531176769.56407998844108.662614204
1176674.50022223844086.2131218321176539.47866781844040.417678096
#Sta/Elev= 30
9655.69177.177359740.59354.507339777.38948.466679797.36246.886969810.59847.62612
9823.81647.03298 9833.7348.228129886.41348.229799929.08845.932959945.50346.11874
9965.21844.2351710001.3637.4955610007.9338.1425210044.0450.9204710076.9552.70935
10093.4159.6060810106.6362.6264210143.4377.9523410201.0999.3250910214.86107.0732
10221.75  107.83 10249.3121.628710256.19126.663610266.52 132.43310273.47134.3643
 10287.4135.506310311.78151.493510315.27 152.56910336.16152.9291 10344.3157.7289
#Mann= 3 , 0 , 0
9655.691   0.085       09655.691   0.085       0 10344.3   0.085       0
#XS Ineff= 2 , 0
       0                               0
Bank Sta=9655.691,10344.3
Exp/Cntr=0.3,0.1

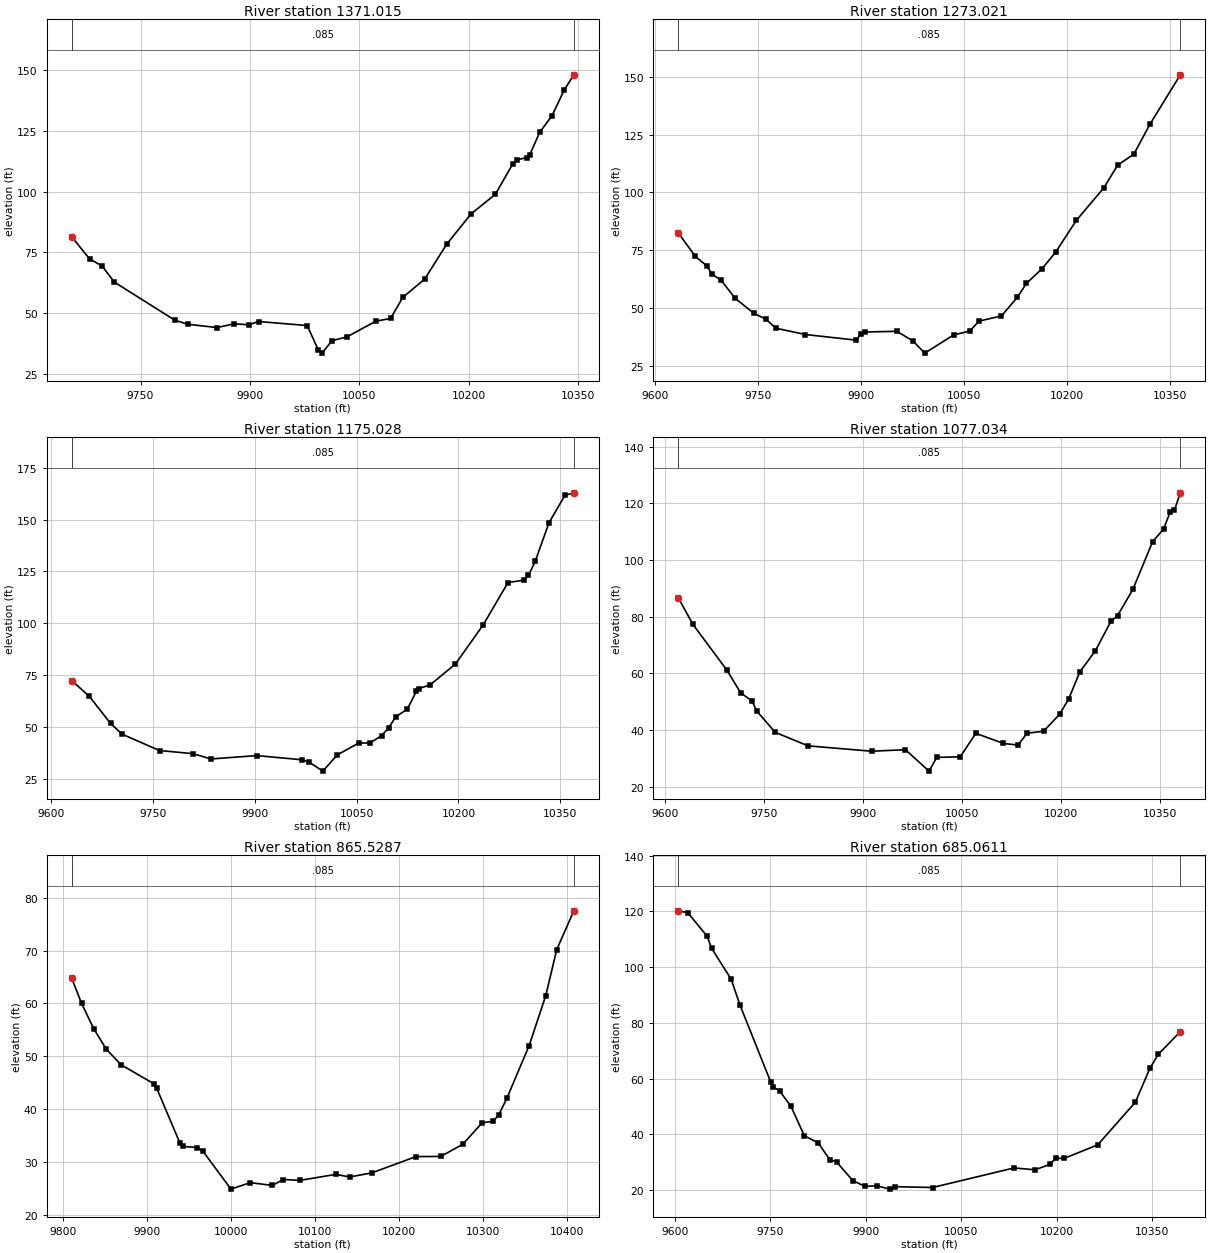
Type RM Length L Ch R = 1 ,1371.015,97.993400,97.993400,97.993400
XS GIS Cut Line= 6
1177243.48645977844112.4454390181176977.79485622844053.431469534
1176939.80873429844039.0743233611176881.97091691844007.477394941
1176845.86290657843994.8358397441176580.24911307843938.697618395
#Sta/Elev= 30
  9655.781.399589680.21672.273519697.13669.460179714.05662.747619797.12347.03258
9814.79345.386419854.91244.002749878.314 45.5582 9898.4745.169799911.967 46.5004
9978.60744.840189993.57434.943349998.927 33.471910012.5538.5896310033.2340.18024
10072.7346.6462310092.94  47.75710109.6456.4357310139.7163.9863810169.7878.34167
10203.1990.8211110236.6298.9471910260.23111.308110266.98113.237710280.48114.1081
10283.85115.234110297.35124.467810314.22131.288910331.09141.948410344.28 148.204
#Mann= 3 , 0 , 0
  9655.7   0.085       0  9655.7   0.085       010344.28   0.085       0
#XS Ineff= 2 , 0
       09922.354                       0
Bank Sta=9655.7,10344.28
Exp/Cntr=0.3,0.1

Type RM Length L Ch R = 1 ,1273.021,97.993300,97.993300,97.993300
XS GIS Cut Line= 6
1177289.59775584 843988.075286411177026.49753302 843919.87948829
1176973.34599168843920.9771960721176887.54187277843948.272571819
1176830.57862533843952.5181993881176576.45699626843908.035615981
#Sta/Elev= 30
9634.42682.493159659.33172.291959676.39168.103979683.21564.690889696.86261.97819
9717.333 54.15369744.62947.648119761.688 45.21569776.72841.22211 9819.6938.50194
9893.52636.068349900.17338.711169906.81639.603659952.851 39.88849976.33535.66954
9993.48130.4573310035.4938.3392910059.0640.00591 10072.344.2802910105.1646.55769
10128.1954.5674110141.3560.5725310164.4367.0370110184.3474.26133 10214.2 87.8821
10254.29101.975110274.36111.7642 10297.9116.5141 10321.5129.532710365.57150.8175
#Mann= 3 , 0 , 0
9634.426   0.085       09634.426   0.085       010365.57   0.085       0
#XS Ineff= 2 , 0
       09922.709                       0
Bank Sta=9634.426,10365.57
Exp/Cntr=0.3,0.1

Type RM Length L Ch R = 1 ,1175.028,97.993400,97.993400,97.993400
XS GIS Cut Line= 6
1177257.82955209843946.9896402211177048.15915871843880.845657186
1176928.47243797843860.3539594541176860.99123946843834.312224372
1176785.75396418843812.3440219921176544.12490603843756.531763589
#Sta/Elev= 30
9629.96872.297369655.95464.651569687.13251.597899704.33446.382919759.37738.51645
9808.62637.003679835.06234.44867  9902.636.076639968.81234.065859979.16533.05507
10000.17  28.57210021.3336.4065210052.79 42.106210069.8842.2229410086.9745.77587
10097.2349.5397910107.48 54.794710124.5458.4584610138.0767.1855710141.45 68.4112
10158.3670.2489310195.56 80.301110236.1499.0220510273.06119.648210296.55120.7706
10303.26123.082310313.33130.062810333.46148.497610356.95161.750110370.11162.9583
#Mann= 3 , 0 , 0
9629.968   0.085       09629.968   0.085       010370.11   0.085       0
#XS Ineff= 2 , 0
       09885.293                       0
Bank Sta=9629.968,10370.11
Exp/Cntr=0.3,0.1

Type RM Length L Ch R = 1 ,1077.034,211.505800,211.505800,211.505800
XS GIS Cut Line= 6
1177296.63601057843926.3455271431177079.46382929843845.965267516
1176887.10442387843723.1794730981176820.40403181843689.385309617
1176730.70793656843662.0650311191176600.67957204843641.147608559
#Sta/Elev= 30
 9619.6886.711869641.81377.305149693.33761.117869714.19453.135759731.57650.18174
9738.52846.706689766.58739.151659816.37634.375819912.635 32.47919963.86733.01241
9999.61925.4478610011.4430.3056410046.8830.4911110070.5238.7959510112.3135.22496
10134.1334.6619610148.5638.8714910173.0939.50743 10197.445.5158210211.1550.91358
10228.0860.4758810251.7468.0052610275.1478.3483110285.1680.3373310308.4889.64495
 10338.3106.477510354.86 110.921 10364.8116.866410371.43117.627510380.31123.7395
#Mann= 3 , 0 , 0
 9619.68   0.085       0 9619.68   0.085       010380.31   0.085       0
#XS Ineff= 2 , 0
       09910.474                       0
Bank Sta=9619.68,10380.31
Exp/Cntr=0.3,0.1

Type RM Length L Ch R = 1 ,865.5287,180.467600,180.467600,180.467600
XS GIS Cut Line= 5
1177282.84343281 843703.524969431177201.59103027843666.509986043
1177125.44900098843642.9166811851177028.93093574843636.482143506
1176697.45687909843612.037154081
#Sta/Elev= 30
9810.18264.740889821.86759.990039836.28855.227459851.13551.367829868.73548.40279
 9907.9744.785549911.40543.920729938.88333.612149942.31732.928239959.49132.72084
 9966.3632.036049999.78924.8433210022.81 26.070710049.1125.5461410062.2626.66311
10081.9926.4974210124.7627.6342110141.2127.1482710167.5327.9139610220.16 30.9979
10249.7731.0276410276.09 33.347510299.1237.4017810312.2837.7014510318.8638.89729
10328.7342.1277910355.0452.0087210374.7861.4484910387.9470.1904410408.2977.51515
#Mann= 3 , 0 , 0
9810.182   0.085       09810.182   0.085       010408.29   0.085       0
#XS Ineff= 2 , 0
       0                               0
Bank Sta=9810.182,10408.29
Exp/Cntr=0.3,0.1

Type RM Length L Ch R = 1 ,685.0611,97.993300,97.993300,97.993300
XS GIS Cut Line= 6
 1177381.7496861843337.027932071 1177235.0306481843381.210094426
1177124.49751157843430.2970997111176966.06019998843558.619515119
 1176900.1946299843568.2231223211176660.25363093843564.484033025
#Sta/Elev= 30
9605.757120.21829620.657119.5709 9651.22111.07999658.012 106.8339688.78695.71907
9702.60986.467599750.98958.790789754.44457.185289764.94955.590959782.64150.12327
9803.87239.490019825.30137.043969843.526  31.002 9854.4630.106179879.97523.43749
9898.95321.373039917.93421.571849937.86420.385789945.91721.27072 10005.120.96625
10133.1327.9931210166.0127.3213810188.97 29.231410198.8231.4248810211.9431.42675
10264.4436.2678710323.5151.5615510346.4763.76202 10359.668.7698210394.1376.87223
#Mann= 3 , 0 , 0
9605.757   0.085       09605.757   0.085       010394.13   0.085       0
#XS Ineff= 2 , 0
       0                               0
Bank Sta=9605.757,10394.13
Exp/Cntr=0.3,0.1

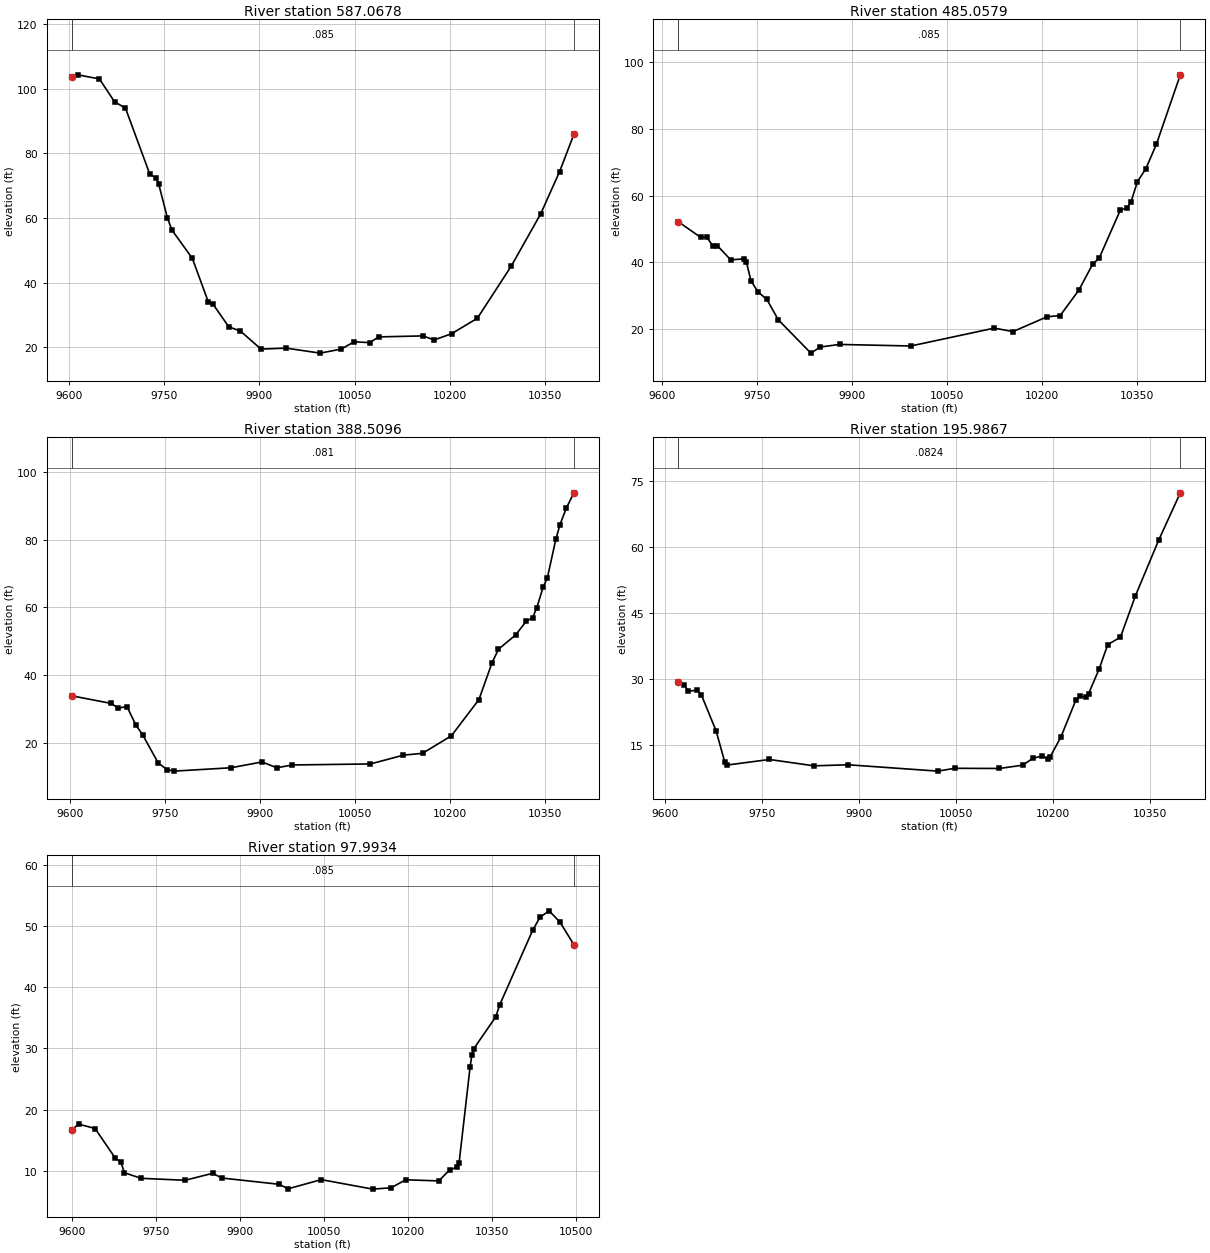
Type RM Length L Ch R = 1 ,587.0678,102.009900,102.009900,102.009900
XS GIS Cut Line= 6
1177379.56719002843278.8152812471177235.00868842843325.630453807
1177053.08603556843405.5070729241176967.93415191843417.722165024
1176772.59501133843483.878381786 1176626.6049041843505.134102811
#Sta/Elev= 30
 9604.44103.72599613.756 104.2469647.978102.98239671.93395.890699689.043 93.9603
9727.38273.555119737.83972.262529741.32570.562869755.26759.920329762.36356.26015
 9794.4147.533399819.33634.200279826.49933.515759851.88326.362349870.01425.09219
 9902.6519.480259941.92919.800379995.89118.2476910028.9519.49807 10049.421.75512
10073.9121.4790910087.9223.2642310157.9523.5668710175.3622.3127610202.8924.24757
10243.5729.0302310296.9745.1601710343.4661.3478310373.1674.3702610395.5485.82425
#Mann= 3 , 0 , 0
 9604.44   0.085       0 9604.44   0.085       010395.54   0.085       0
#XS Ineff= 2 , 0
       0                               0
Bank Sta=9604.44,10395.54
Exp/Cntr=0.3,0.1

Type RM Length L Ch R = 1 ,485.0579,96.548300,96.548300,96.548300
XS GIS Cut Line= 6
1177301.00247093843149.8627144011177089.06766043843240.825161681
1176912.61461362843371.6915798651176837.86730916843413.961278491
1176736.62889011843451.0437403881176591.63981138843476.818520812
#Sta/Elev= 30
9625.47452.158489660.843 47.46639670.71847.482949680.34944.803869687.30544.95455
 9708.3640.693589729.60541.022549733.14639.977359740.22734.475259750.92331.17964
9765.39128.811789783.47722.692789834.82612.710749849.69714.549359880.14515.32031
9992.54614.8530910124.2520.2175110153.7719.1794810207.5223.6201610228.2623.97883
10257.5431.5561510279.7439.4821210289.8141.2080910323.3655.7176610333.4356.21021
10340.1458.1688410350.2164.1849110363.48 68.078410380.0275.3502210417.8896.25147
#Mann= 3 , 0 , 0
9625.474   0.085       09625.474   0.085       010417.88   0.085       0
#XS Ineff= 2 , 0
       0                               0
Bank Sta=9625.474,10417.88
Exp/Cntr=0.3,0.1

Type RM Length L Ch R = 1 ,388.5096,192.522900,192.522900,192.522900
XS GIS Cut Line= 6
1177252.81270065843074.3308959681177023.61376818843169.916534043
1176830.96483097843315.9597041321176759.75316761843358.239691885
1176660.88778064843394.3471313771176548.49261856843416.055933866
#Sta/Elev= 30
 9602.0333.881459664.74231.621949675.21830.254479689.31630.704639703.41425.22781
9713.98822.41569 9738.6614.073799752.94512.057549763.75911.656349853.72512.65008
9902.85914.366259926.05512.649289950.80213.4754110074.1613.7748110126.3116.37339
10156.4616.9121710202.1322.0783610245.6732.7822410266.2843.5997610276.5847.64561
 10303.651.8275110320.4255.8836510330.5256.9245110337.2559.9401710347.2566.04309
10353.8968.7423510367.1780.0558510373.8184.4162510383.7889.26252 10395.793.79447
#Mann= 3 , 0 , 0
 9602.03   0.081       0 9602.03   0.081       0 10395.7   0.081       0
#XS Ineff= 2 , 0
       0                               0
Bank Sta=9602.03,10395.7
Exp/Cntr=0.3,0.1

Type RM Length L Ch R = 1 ,195.9867,97.993300,97.993300,97.993300
XS GIS Cut Line= 6
1177196.15343613843070.5463039651176860.56053302843103.487938628
1176857.15256131843101.0823115461176768.74464294843101.312490077
1176705.25995361843104.1435413191176421.98082217843128.600053386
#Sta/Elev= 30
9619.80429.244619629.09328.550019635.68627.241899648.87327.403859655.466 26.4354
9678.54218.163739691.72811.179039695.02510.413469760.957  11.6889830.18610.24646
9882.93110.4860410021.899.04218710048.149.68318510117.12 9.6475810153.3410.39174
10169.8112.0208510182.9812.4061710192.8611.8594310196.1512.3422310212.62 16.8175
10235.6725.1709510242.2526.0771510252.13  25.84410255.4226.6454910271.8932.29077
10285.0637.8024210304.8239.4842510327.8748.86013 10364.161.5741610397.5272.30549
#Mann= 3 , 0 , 0
9619.804  0.0824       09619.804  0.0824       010397.52  0.0824       0
#XS Ineff= 2 , 0
       0                               0
Bank Sta=9619.804,10397.52
Exp/Cntr=0.3,0.1

Type RM Length L Ch R = 1 , 97.9934,0.000000,0.000000,0.000000
XS GIS Cut Line= 6
1177221.96931188842988.8080480121176925.97833276842998.390489802
1176856.06240744843004.4084739541176741.67355893  843002.3196585
1176653.41360514843003.3368972071176325.97222671843017.815434401
#Sta/Elev= 30
9599.12116.651029611.22217.629069640.764 16.90829676.87312.05936 9686.7211.40198
9693.285 9.678269722.8288.769129 9801.618.4521069850.8489.5898399867.2618.816861
9969.3087.7982289985.7147.06069910044.788.55770510136.657.00404910169.477.222374
10195.74 8.5304410254.858.34597510274.5610.1988110287.6910.5619810290.9811.30313
10310.6827.0030110313.9628.9956110317.2529.9511310356.6635.1796210363.2237.04928
10422.3449.2797110435.4751.4200810451.8952.47047 10471.650.5721910495.9546.93706
#Mann= 3 , 0 , 0
9599.121   0.085       09599.121   0.085       010495.95   0.085       0
#XS Ineff= 2 , 0
       0                               0
Bank Sta=9599.121,10495.95
Exp/Cntr=0.3,0.1